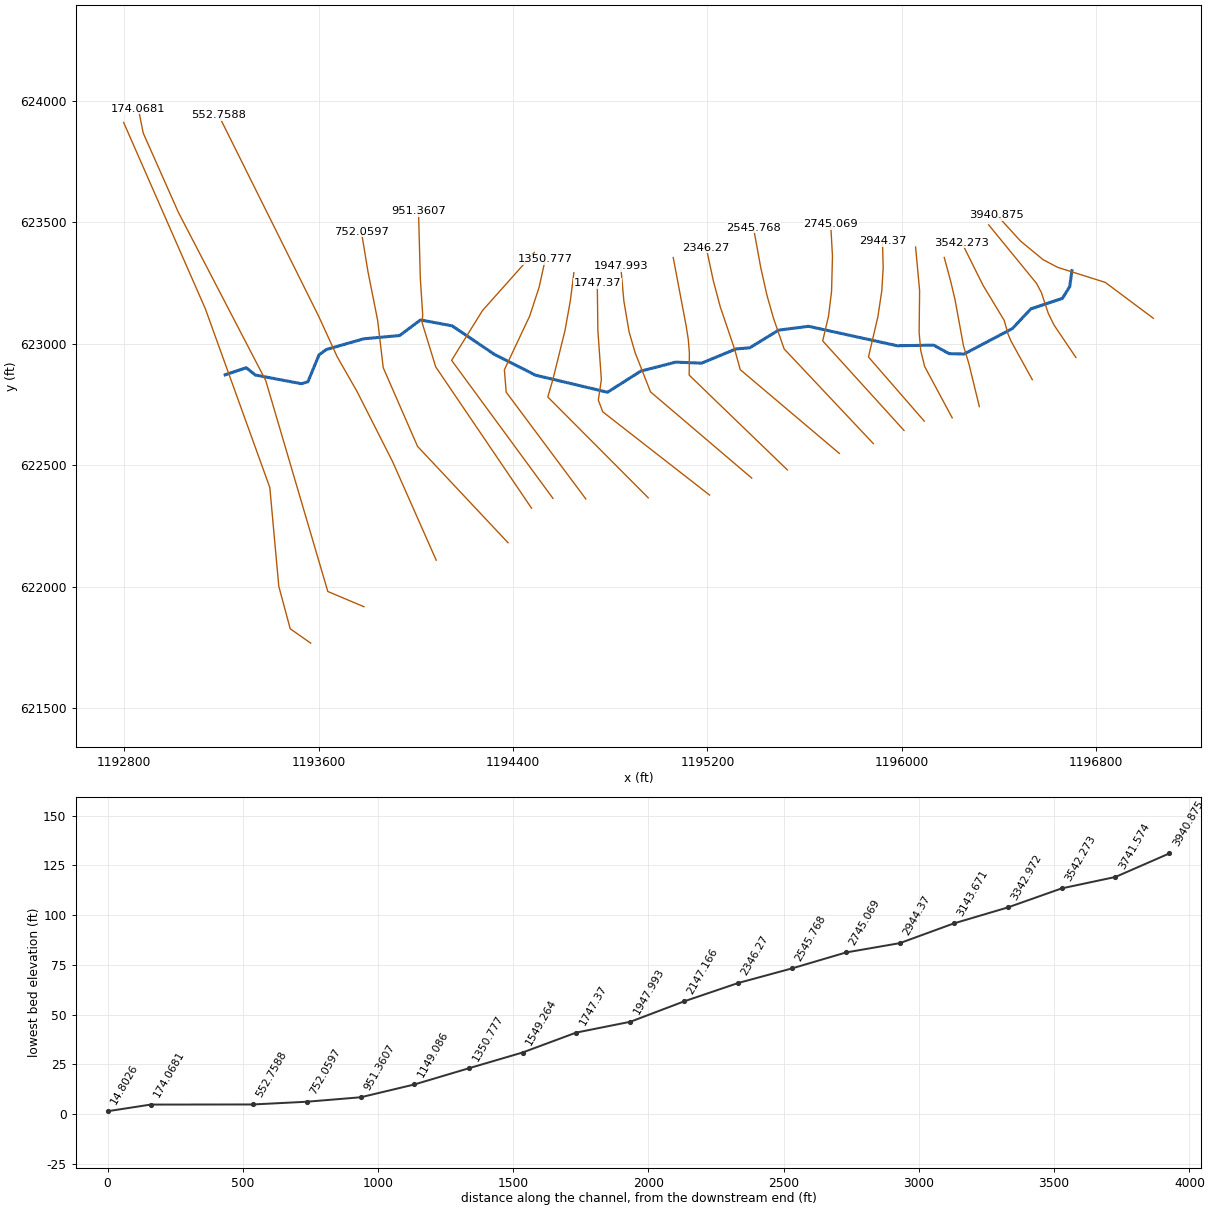
--- 312_ras.prj (project) ---

Proj Title=312
Current Plan=p01
Default Exp/Contr=0.3,0.1
English Units
Geom File=g01
Flow File=f01
Plan File=p01
Y Axis Title=Elevation
X Axis Title(PF)=Main Channel Distance
X Axis Title(XS)=Station
BEGIN DESCRIPTION:
RFD model 312 exported to HEC-RAS
END DESCRIPTION:

--- 312_ras.p01 (plan) ---

Plan Title=Plan 01
Program Version=4.10
Short Identifier=Plan 01
Geom File=g01
Flow File=f01
Subcritical Flow
Calc Critical at every XS
Secant Critical Depth

--- 312_ras.f01 (steady flow) ---

Flow Title=Flow 01
Program Version=5.01
Number of Profiles= 5
Profile Names=10yr,25yr,50yr,100yr,500yr
River Rch & RM=312,20,3940.875
  671.63  869.46 1055.96 1223.49 1595.35
River Rch & RM=312,20,3741.574
  680.17  882.14 1071.82 1244.19 1626.23
River Rch & RM=312,20,3542.273
  684.93  889.22 1080.67 1255.75 1643.51
River Rch & RM=312,20,3342.972
  689.63  896.22 1089.43 1267.22 1660.67
River Rch & RM=312,20,3143.671
  693.22  901.57 1096.11 1275.97  1673.8
River Rch & RM=312,20, 2944.37
  697.49  907.93 1104.08 1286.41 1689.45
River Rch & RM=312,20,2745.069
  727.63  953.04 1160.56 1360.71 1801.43
River Rch & RM=312,20,2545.768
  736.83  966.86 1177.88 1383.58 1836.09
River Rch & RM=312,20, 2346.27
   737.8  968.33 1179.72 1386.02 1839.78
River Rch & RM=312,20,2147.166
  742.97  976.11 1189.47 1398.92 1859.36
River Rch & RM=312,20,1947.993
   744.9  979.01 1193.11 1403.73 1866.67
River Rch & RM=312,20, 1747.37
  745.86  980.45 1194.92 1406.13 1870.32
River Rch & RM=312,20,1549.264
  755.03  994.29 1212.27 1429.13 1905.33
River Rch & RM=312,20,1350.777
  756.28  996.18 1214.64 1432.28 1910.12
River Rch & RM=312,20,951.3607
  757.22  997.59 1216.42 1434.63 1913.72
River Rch & RM=312,20,752.0597
  758.78  999.95 1219.37 1438.55 1919.69
River Rch & RM=312,20,552.7588
  768.63 1014.85 1238.07  1463.4 1957.64
River Rch & RM=312,20,174.0681
  774.09 1023.11 1248.45 1477.22 1978.78
Boundary for River Rch & Prof#=312,20,1
Up Type= 0
Dn Type= 2
Boundary for River Rch & Prof#=312,20,2
Up Type= 0
Dn Type= 2
Boundary for River Rch & Prof#=312,20,2
Up Type= 0
Dn Type= 2
Boundary for River Rch & Prof#=312,20,2
Up Type= 0
Dn Type= 2
Boundary for River Rch & Prof#=312,20,2
Up Type= 0
Dn Type= 2

--- 312_ras.g01 (geometry) ---

Geom Title=312
Program Version=4.10

River Reach=312,20
Reach XY= 30
 1196700.5831711623301.5902642611196691.41650522623235.756950706
 1196661.4165127623187.4236326071196531.41654977623144.090315863
1196455.58323646623063.2570086871196256.41662562622958.257045597
1196194.74997714 622959.923713551196131.41666353622994.923705012
1195981.41670769622992.4237100331195616.41681772623072.423696831
1195493.08352023623056.5903717431195374.75021979622984.090396702
1195317.25023657622979.0903998321195176.41694307622920.757087871
1195069.75030801622924.9237563761194926.41701591622888.257104725
1194788.93165824622801.0544532241194492.18583483622871.474137694
1194323.11309889622957.1376572551194149.53175664 623074.36142081
1194019.31369963 623098.595353411193933.48038968 623034.42870824
1193785.98043287623021.0953831521193631.81381038622976.928734004
 1193601.8138186622955.262074634 1193555.9804956622844.428775549
 1193529.3138366622836.0954454541193339.31389365622871.928773612
 1193301.8139056622901.9287658041193215.14726368622872.762110278

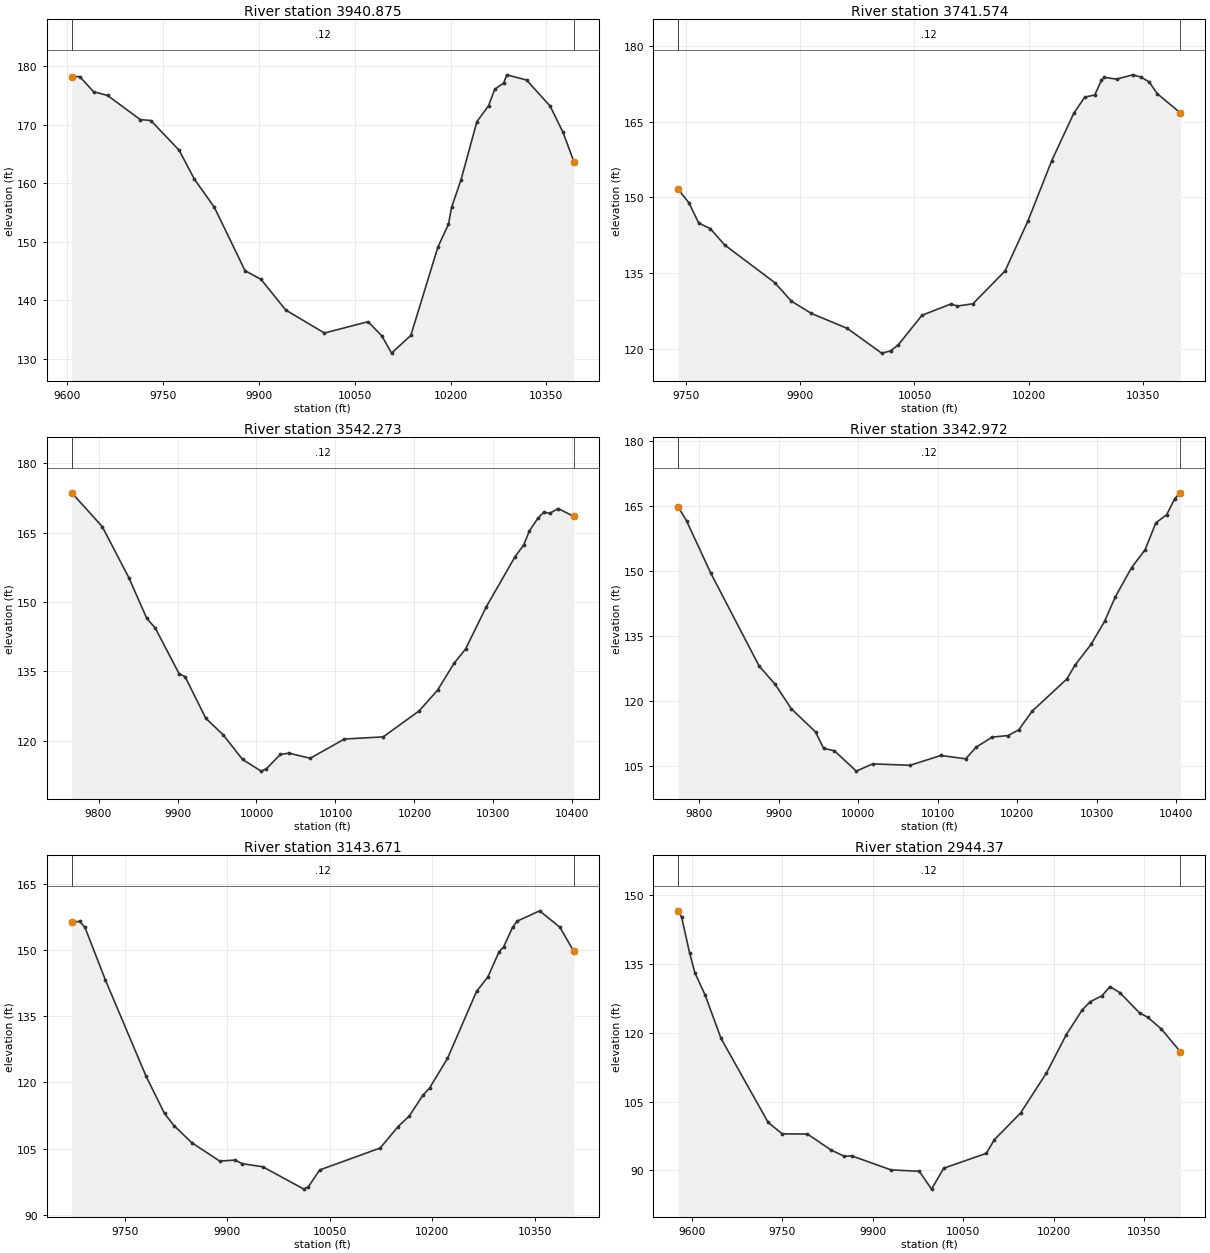
Type RM Length L Ch R = 1 ,3940.875,199.300900,199.300900,199.300900
XS GIS Cut Line= 6
1197035.37708237623105.6833117541196837.74269571 623253.18892108
1196641.98139682 623315.032474541196582.05968514623346.549657153
1196489.05655144 623423.203281671196391.83900889623529.861367427
#Sta/Elev= 30
9606.819178.22539619.179 178.2649640.995175.67699662.811175.03749714.174170.9008
9730.604 170.7519774.947165.67089798.823160.72469830.093155.92049878.196145.0714
9903.391143.57249941.903138.346110002.48134.412410070.87 136.34710092.53133.9165
10107.63130.972810137.85134.006110180.14149.081410196.76153.010210201.67155.9114
10216.42160.609610241.32170.560110259.69173.295310269.15176.080710283.33177.1766
10288.06178.561610319.01177.674510355.99173.2247 10376.3168.702210393.14163.7348
#Mann= 3 , 0 , 0
9606.819    0.12       09606.819    0.12       010393.14    0.12       0
#XS Ineff= 2 , 0
       0                10056.05       0
Bank Sta=9606.819,10393.14
Exp/Cntr=0.3,0.1

Type RM Length L Ch R = 1 ,3741.574,199.301000,199.301000,199.301000
XS GIS Cut Line= 6
1196716.86504387622944.1427593721196626.70544005  623077.7040259
1196603.18085123623125.7205788021196574.58307974 623211.93519602
1196554.67912142623249.1877027881196358.01340073623489.812974484
#Sta/Elev= 30
9740.071151.59739753.917148.98249766.949144.93319782.105143.82819800.899 140.605
9866.679133.12529888.464129.46059914.875 127.0089961.949124.044510006.84119.1524
10018.65119.588710028.93120.832110059.75126.6441 10097.9128.901310106.12128.4806
10126.65128.932810168.82135.444110198.88145.371410230.05 157.30710258.98166.7013
10273.47169.9038 10286.5170.318710295.18173.218110299.05173.8035   10315173.4608
10336.43174.310710347.14173.857510357.69172.923310368.56170.5614 10398.7166.7787
#Mann= 3 , 0 , 0
9740.071    0.12       09740.071    0.12       0 10398.7    0.12       0
#XS Ineff= 2 , 0
       0                               0
Bank Sta=9740.071,10398.7
Exp/Cntr=0.3,0.1

Type RM Length L Ch R = 1 ,3542.273,199.300900,199.300900,199.300900
XS GIS Cut Line= 6
 1196537.4206676622852.7742925421196449.52169395623012.148558917
1196437.84766327623039.9633426521196421.68041416623096.866141364
 1196335.1539365623240.1256244161196247.39402561623416.248458702
#Sta/Elev= 30
9766.098173.59469804.643166.29729838.364155.23599860.844146.52069872.085144.2629
9902.058134.45519909.552133.84539935.779124.83359957.748121.26649982.423115.9164
10005.92113.3966 10012.6113.9282 10030.2116.997210041.08117.284810068.06116.1784
 10111.3120.336610160.44120.806410205.86126.412310229.22130.892510250.25136.7468
10264.73139.805510290.94148.936610327.45 159.79310338.36162.318710345.63165.3843
10356.54 168.16210363.81169.430910371.08169.134510381.99170.198510401.84 168.481
#Mann= 3 , 0 , 0
9766.098    0.12       09766.098    0.12       010401.84    0.12       0
#XS Ineff= 2 , 0
       0                               0
Bank Sta=9766.098,10401.84
Exp/Cntr=0.3,0.1

Type RM Length L Ch R = 1 ,3342.972,199.301000,199.301000,199.301000
XS GIS Cut Line= 6
1196319.45825586622741.7934314981196276.17415893622919.332301862
1196254.36385837622991.0868081831196219.18335316623182.718777837
1196202.06113025623255.2795346261196174.98350432623355.824666728
#Sta/Elev= 30
9773.681164.72329784.198161.51169814.591149.47889875.376128.05989895.637123.8186
9915.899118.17759946.291112.86969956.422109.08159970.134108.49229997.559103.8144
10018.17105.485910065.15 105.16210103.96 107.42710135.08106.6536 10148.4 109.364
10168.45111.674710188.53 112.01910201.91 113.37310218.64117.634110262.41125.0919
10272.52128.256310292.75133.066810309.67138.341710323.26 144.01610343.65150.7406
10360.64154.861710374.23161.083610387.82162.958910398.01166.677110404.95167.9984
#Mann= 3 , 0 , 0
9773.681    0.12       09773.681    0.12       010404.95    0.12       0
#XS Ineff= 2 , 0
       0                               0
Bank Sta=9773.681,10404.95
Exp/Cntr=0.3,0.1

Type RM Length L Ch R = 1 ,3143.671,199.300900,199.300900,199.300900
XS GIS Cut Line= 6
1196207.71052876622695.6384923311196094.32609871622907.002905264
1196078.19288832622972.7664123481196071.59961447 623047.22634837
1196073.60948834623218.5767806921196057.07800218623398.713352054
#Sta/Elev= 30
9672.577156.33769684.426 156.4119691.872155.06999721.657143.21499781.226121.4057
9808.328112.94019822.208110.19929848.242106.31789889.196102.15199911.534102.4011
9921.752101.58779952.155 100.87410012.2295.8141310018.83  96.34310035.28100.1486
 10123.9105.122510150.14109.987210166.55112.373510186.24117.045110196.08118.6764
10222.33125.391510265.03140.614710281.46143.837510297.88149.571910304.47150.6369
10317.66155.093710324.26156.481110357.24158.823510387.04155.087110407.31 149.615
#Mann= 3 , 0 , 0
9672.577    0.12       09672.577    0.12       010407.31    0.12       0
#XS Ineff= 2 , 0
       0                               0
Bank Sta=9672.577,10407.31
Exp/Cntr=0.3,0.1

Type RM Length L Ch R = 1 , 2944.37,199.301000,199.301000,199.301000
XS GIS Cut Line= 6
1196092.74106833622682.1126734471195863.06539315622946.179327965
1195901.70838889623111.0416219981195917.97452345623219.064812511
1195923.66911441623313.9344473631195920.62128532623423.093426019
#Sta/Elev= 30
9577.238146.56059582.913145.17079595.958137.45889604.818133.07429622.047128.1622
9648.136118.78949726.403100.45019749.79697.966339791.62697.928049830.75994.43883
  9852.593.097079865.54593.15115 9929.9790.121579977.18589.80081 9997.4285.92276
10017.6490.4888910088.3593.7167310101.7696.7083210145.05102.5065 10188.1 111.242
10221.07119.608310247.37124.963210260.51126.747910280.23128.059310293.38 130.042
 10309.8128.732510342.61124.294210355.73123.403210378.72120.814210410.09115.8608
#Mann= 3 , 0 , 0
9577.238    0.12       09577.238    0.12       010410.09    0.12       0
#XS Ineff= 2 , 0
       09922.551                       0
Bank Sta=9577.238,10410.09
Exp/Cntr=0.3,0.1

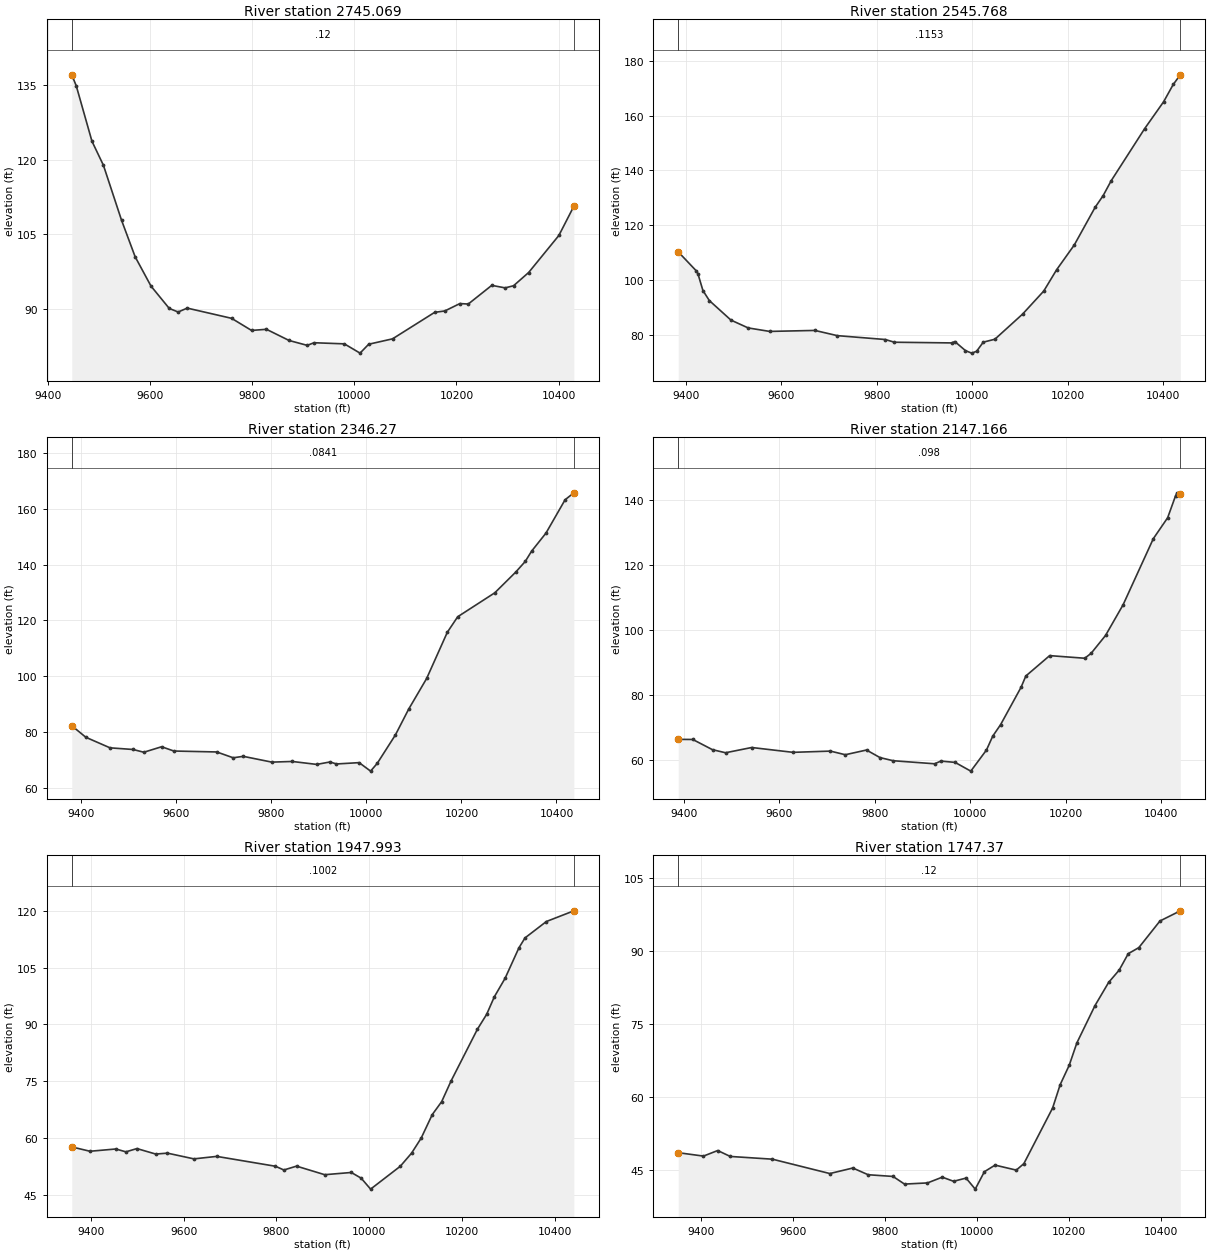
Type RM Length L Ch R = 1 ,2745.069,199.300900,199.300900,199.300900
XS GIS Cut Line= 6
1196009.33185193622643.7895199661195674.63116077623012.374506906
1195698.73987973623114.2839938851195711.17061269623216.729736373
1195714.91426811 623360.953030841195707.54885939623493.178750813
#Sta/Elev= 30
9447.198136.98329456.001 134.7739486.698  123.68 9509.18118.85459544.634107.8442
9571.224100.53659602.245 94.65929637.98890.183169655.42589.465649673.15290.24829
9759.99688.201599799.03885.77533 9828.2686.001659872.57783.76005 9908.0382.78421
9921.32583.30953 9980.7183.0866310011.4181.2280810028.3383.0090810075.02 84.0902
10157.5589.4041710177.2689.6736610206.8391.1547210223.2591.0634610269.1894.80303
10295.4394.3024410311.8494.7262610341.3997.3765310400.57 104.80510429.87110.6515
#Mann= 3 , 0 , 0
9447.198    0.12       09447.198    0.12       010429.87    0.12       0
#XS Ineff= 2 , 0
       09893.334                       0
Bank Sta=9447.198,10429.87
Exp/Cntr=0.3,0.1

Type RM Length L Ch R = 1 ,2545.768,199.498600,199.498600,199.498600
XS GIS Cut Line= 6
1195883.09087574622589.6862444731195515.95695159622979.415613472
1195472.01519576623105.9019827691195445.19517916623200.424693778
1195419.65315044623314.3210189491195389.67962563623478.522057608
#Sta/Elev= 30
9384.617110.23739422.825103.22279425.839102.24429436.347 96.09969449.76392.44126
9494.94285.312729531.00182.450379576.07481.169339670.72781.531999717.70679.62658
9818.18578.211219837.324  77.2199956.905 76.97039963.80477.460639986.09874.15063
    999973.2385110009.3573.9088210023.3277.2475310047.5678.3098410105.6387.49344
10149.97 95.9195 10176.9103.696910213.88112.750710257.59126.531710274.36130.7924
10291.03136.183710361.07155.218210401.09165.1211 10421.1171.406310435.91174.9229
#Mann= 3 , 0 , 0
9384.617  0.1153       09384.617  0.1153       010435.91  0.1153       0
#XS Ineff= 2 , 0
       09882.942                       0
Bank Sta=9384.617,10435.91
Exp/Cntr=0.3,0.1

Type RM Length L Ch R = 1 , 2346.27,199.103300,199.103300,199.103300
XS GIS Cut Line= 6
1195743.32408071622549.1087878641195335.29521132622894.017169148
1195312.26262906622977.7146302311195253.20650566623152.035305902
1195224.31579521 623260.64837493 1195195.2137903623396.642024532
#Sta/Elev= 30
9379.93682.185059409.64178.033089460.46274.249939508.87673.657469531.61272.66877
9569.019 74.64079594.79473.104019685.00972.77016 9719.6570.677989740.85671.19483
9800.96469.120179843.95969.35569 9895.5168.295699923.45569.178919937.06668.45638
9984.70568.9346610008.8565.8855410022.8668.6887810061.0778.8897110088.8588.11213
 10126.899.1616910170.34115.762610192.15121.323110270.23 129.92810314.17137.3464
 10334.3141.186410347.72 144.89210377.92151.367410418.18163.343410436.58165.8297
#Mann= 3 , 0 , 0
9379.936  0.0841       09379.936  0.0841       010436.58  0.0841       0
#XS Ineff= 2 , 0
       09876.987                       0
Bank Sta=9379.936,10436.58
Exp/Cntr=0.3,0.1

Type RM Length L Ch R = 1 ,2147.166,199.173400,199.173400,199.173400
XS GIS Cut Line= 6
1195529.16528186622481.4796934721195125.12804028622871.430449054
1195125.97106716 622962.965385811195121.51677534  623017.7928022
1195112.37692937623075.4062216131195059.41170338623355.529179245
#Sta/Elev= 30
9388.45666.456819418.96866.421639460.219 63.28449487.57662.346239542.29263.95864
9628.92562.473859707.15362.853099738.35661.739979782.74363.184079811.08960.85607
9838.66859.896239925.30158.962289938.64659.791329968.35559.3815310001.1656.70418
10033.9863.1850910047.1267.4430110063.5870.9738510106.4682.4535810116.4385.91095
10166.3392.1697310239.8891.3672910253.2592.8911410283.34 98.361710320.12107.7776
10383.47 128.09210413.46134.511810430.12141.292310433.45142.158210439.96141.6772
#Mann= 3 , 0 , 0
9388.456   0.098       09388.456   0.098       010439.96   0.098       0
#XS Ineff= 2 , 0
       09880.056                       0
Bank Sta=9388.456,10439.96
Exp/Cntr=0.3,0.1

Type RM Length L Ch R = 1 ,1947.993,200.622600,200.622600,200.622600
XS GIS Cut Line= 6
1195382.63557738622447.665146291 1194966.0152148622802.562017098
1194902.73867229622963.5620234311194877.81208611623049.500115722
1194856.19083208623177.0980568981194843.46457422623319.492363885
#Sta/Elev= 30
9358.98357.59343 9398.2756.447379453.92357.046029475.67756.293659499.45857.15318
9539.93355.70847 9565.2355.949149622.21154.436169671.47755.091339797.96252.48567
9816.15451.498789843.49652.517299904.20950.252999961.48350.841179982.72949.34458
10003.1246.4411710067.0752.4770610091.3955.9407210112.0559.9068710136.0166.13199
10156.3469.5642810176.5775.0240210233.3888.7006310253.2792.6271110269.8597.26399
10293.06102.162610322.74110.177210335.91 112.81810382.03117.153510441.21119.9755
#Mann= 3 , 0 , 0
9358.983  0.1002       09358.983  0.1002       010441.21  0.1002       0
#XS Ineff= 2 , 0
       09876.209                       0
Bank Sta=9358.983,10441.21
Exp/Cntr=0.3,0.1

Type RM Length L Ch R = 1 , 1747.37,198.106900,198.106900,198.106900
XS GIS Cut Line= 6
1195209.05423519622377.7817487721194769.46512175622720.435826927
1194751.15622443622768.7415312081194763.70283544622853.228104144
1194749.31855565623054.2812148331194746.81933036623248.961492807
#Sta/Elev= 30
9350.90948.489029405.68847.789189436.64448.932079463.925 47.71659555.44147.15285
9680.23544.196039730.15745.335019763.43143.951529817.50843.600549842.46742.02671
9892.38542.266589924.49443.451449949.05442.601459976.18343.261829996.08440.98889
10015.98 44.5728 10039.245.93173 10085.344.9027410101.7546.2360310164.2457.69159
10180.6962.5076210200.4366.5204610216.8771.0851110256.3278.7773510285.8683.53389
10308.84 86.076310328.5389.45594 10351.590.7020610397.4396.1845910441.6298.27502
#Mann= 3 , 0 , 0
9350.909    0.12       09350.909    0.12       010441.62    0.12       0
#XS Ineff= 2 , 0
       09916.746                       0
Bank Sta=9350.909,10441.62
Exp/Cntr=0.3,0.1

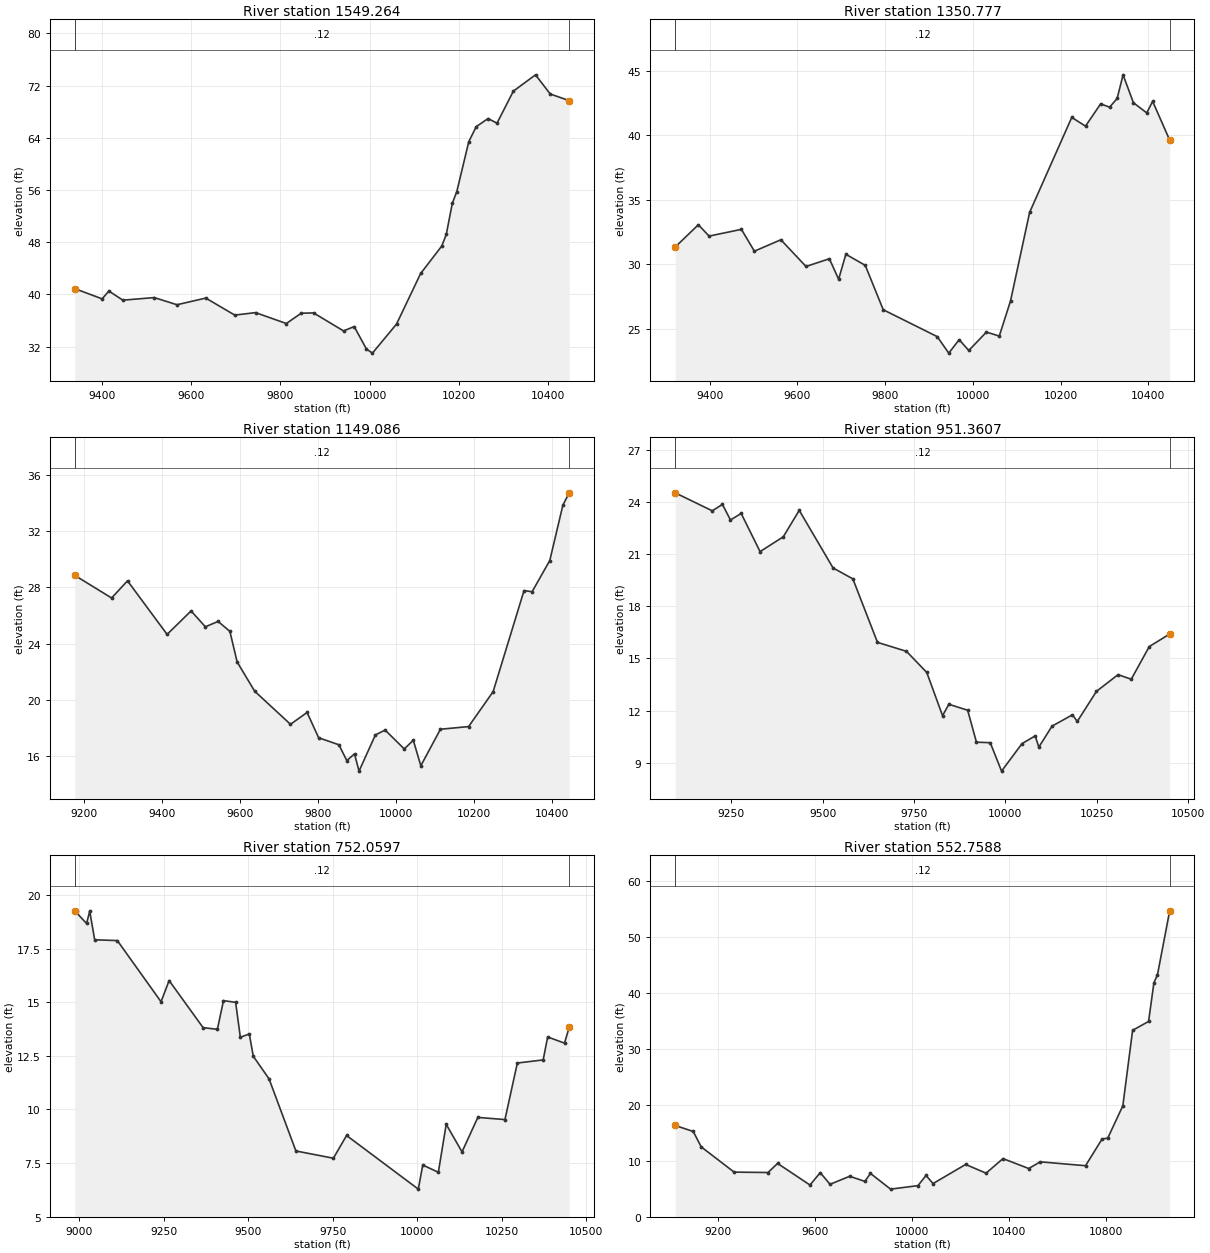
Type RM Length L Ch R = 1 ,1549.264,198.486300,198.486300,198.486300
XS GIS Cut Line= 6
1194956.57228282622366.5102330451194543.22771576622781.539424345
1194564.01494074622852.9730345011194613.66602081623053.749594763
1194635.87118837 623176.799882651194650.54559991623292.920805767
#Sta/Elev= 30
9338.85340.884979400.27939.31428 9415.2640.513699446.77239.115459517.12939.51342
9568.06338.415189632.74239.436749697.71436.826479744.325 37.20749813.47435.53575
9846.60837.113439874.50437.163939941.68834.401459965.60635.070029992.94231.63762
10006.5230.99827 10060.635.4572410114.6743.2059410161.9947.4100910172.1349.18844
10185.65 53.953110195.7955.7718210222.5963.4045110239.2665.7084110265.93 66.9554
10285.9466.2430610322.6171.1554610372.2873.6552710405.3570.7148710447.9169.70305
#Mann= 3 , 0 , 0
9338.853    0.12       09338.853    0.12       010447.91    0.12       0
#XS Ineff= 2 , 0
       09928.802                       0
Bank Sta=9338.853,10447.91
Exp/Cntr=0.3,0.1

Type RM Length L Ch R = 1 ,1350.777,201.691400,201.691400,201.691400
XS GIS Cut Line= 6
1194699.58172423622362.0016267451194371.88859868622801.486446276
1194364.50220722622893.646052405 1194468.4091824623114.070684999
1194507.33196047623232.8530748341194532.72613537623347.927400321
#Sta/Elev= 30
9321.40731.332169374.09833.061659398.653 32.18089472.31732.705719501.87731.00759
9562.25231.895599619.64629.819569672.84830.420559693.97828.826139710.44330.76975
9754.69729.906949795.62126.45994 9918.7224.370239945.05123.087259968.762 24.1294
9990.713 23.293310030.9624.7220710060.2324.4136210085.8427.1395110129.4434.02758
10225.4841.4035210256.8240.7246210291.3242.4545810311.8442.1988110328.9542.87385
10342.47  44.71210366.0942.5421510396.4641.7543810409.8642.6506910448.7439.64104
#Mann= 3 , 0 , 0
9321.407    0.12       09321.407    0.12       010448.74    0.12       0
#XS Ineff= 2 , 0
       09881.507                       0
Bank Sta=9321.407,10448.74
Exp/Cntr=0.3,0.1

Type RM Length L Ch R = 1 ,1149.086,197.725100,197.725100,197.725100
XS GIS Cut Line= 5
 1194564.3235355622364.2559299021194147.27745351622932.340322629
1194189.29330021623000.1793439691194274.53090379623137.566386595
1194487.67722854623376.438042358
#Sta/Elev= 30
9177.57528.861779271.95127.252969312.652 28.47289414.05124.663859475.45226.33192
9512.082 25.20439544.64225.586349574.82724.879139593.48222.701599638.252 20.6274
 9730.0618.272249772.56319.112719802.13217.314519853.96316.816859874.31315.69333
9894.023 16.1673  9905.614.941499947.49317.514099972.40417.86254 10021.416.52002
10044.57 17.134510063.8715.3252610114.0717.9188710186.2418.1100110249.02 20.5924
10328.1727.7791110348.8627.6977910394.1329.91694 10427.733.8580410443.9334.73011
#Mann= 3 , 0 , 0
9177.575    0.12       09177.575    0.12       010443.93    0.12       0
#XS Ineff= 2 , 0
       09880.433           10112       0
Bank Sta=9177.575,10443.93
Exp/Cntr=0.3,0.1

Type RM Length L Ch R = 1 ,951.3607,199.301000,199.301000,199.301000
XS GIS Cut Line= 6
1194476.40571278622323.6784732641194081.90266228622905.288684875
 1194026.0953621 623086.542266921194028.26944956623120.078469664
1194018.44632086 623271.299274341194011.03638643 623546.04303439
#Sta/Elev= 30
9096.89224.517919198.20723.483919225.95723.852089248.01522.956869277.23823.33426
 9329.0321.13987 9392.4621.991279436.06823.511419528.55620.202539582.74919.57371
9650.14415.925169729.43115.409429784.932 14.19699828.10211.710339845.26612.36837
9896.75912.025449920.78910.19072 9958.5510.16025 9989.448.52657710045.3510.10576
10081.5110.5526110091.389.90585210127.5411.1118810183.4211.7637610196.5511.38174
10249.0613.1106510308.1314.0695910344.2413.8076310393.4715.6839110449.3316.40642
#Mann= 3 , 0 , 0
9096.892    0.12       09096.892    0.12       010449.33    0.12       0
#XS Ineff= 2 , 0
       0 9854.32        10131.97       0
Bank Sta=9096.892,10449.33
Exp/Cntr=0.3,0.1

Type RM Length L Ch R = 1 ,752.0597,199.300900,199.300900,199.300900
XS GIS Cut Line= 6
1194379.47067755622181.6573750821194007.13330391622578.127757683
1193865.81126231622902.0358968971193842.95936111623096.243694678
1193803.05875844 623297.275984571193775.96558291623461.359865442
#Sta/Elev= 30
8986.09819.256599021.136 18.66679030.405 19.24349045.09917.906829112.194   17.87
9241.59215.019239265.55516.005599366.19813.811599408.47313.734559426.47615.07096
9462.48314.991959476.42613.36317 9502.9913.518229514.76612.478679561.35411.42815
9640.9598.0648049751.9247.7271839791.071  8.785910003.476.28649110016.637.408973
10062.83 7.0716510086.089.30735110132.918.02159310179.749.62954210260.019.527336
10296.7312.1635810373.2112.3082710386.5113.3772410436.3913.0910710450.39 13.8356
#Mann= 3 , 0 , 0
8986.098    0.12       08986.098    0.12       010450.39    0.12       0
#XS Ineff= 2 , 0
       09873.649        10212.21       0
Bank Sta=8986.098,10450.39
Exp/Cntr=0.3,0.1

Type RM Length L Ch R = 1 ,552.7588,378.690700,378.690700,378.690700
XS GIS Cut Line= 6
1194083.88260671622109.7877750471193904.72346234622514.664803594
1193757.85944659622804.4738937321193676.28859621 622947.13933064
1193599.00561056623116.0613462181193187.96328428623942.158737078
#Sta/Elev= 30
9022.44616.302019096.89215.226989129.59412.478439265.5137.9573419405.4337.883957
9444.8989.5134059578.4725.6480889620.9337.8602519661.392 5.771899742.3097.213823
9805.2426.2972169827.9177.7299089911.0614.91245310024.295.53877510057.497.365244
 10086.3  5.9042   102219.32793710305.187.767189 10374.910.3735910481.168.603215
 10528.8 9.7968410715.689.101545   1078413.8889110807.2914.0330810869.5819.82211
10909.8933.3264210975.8534.9183110997.8341.8444711012.4943.26752 11062.954.71022
#Mann= 3 , 0 , 0
9022.446    0.12       09022.446    0.12       0 11062.9    0.12       0
#XS Ineff= 2 , 0
       09857.261        10297.93       0
Bank Sta=9022.446,11062.9
Exp/Cntr=0.3,0.1

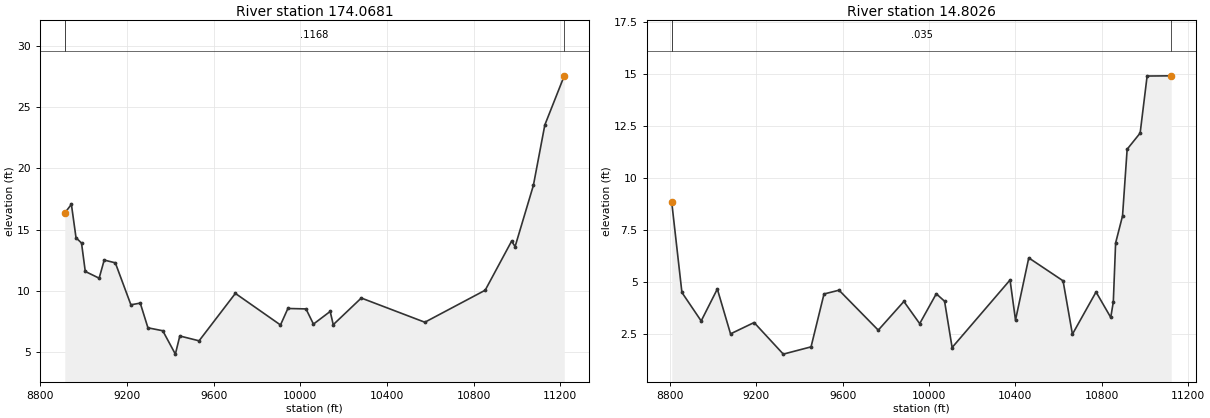
Type RM Length L Ch R = 1 ,174.0681,159.265500,159.265500,159.265500
XS GIS Cut Line= 6
1193786.57596654621918.1202755571193637.74960911621980.958070904
1193382.19072673622849.2636282441193022.53949326 623541.67628336
1192878.00675458623867.715251997 1192857.8393957623968.552046433
#Sta/Elev= 30
8912.22916.345418942.84317.057898964.21114.33304 8989.5813.901259006.94611.58509
9071.04911.035729094.37312.514349145.71112.286599217.5848.8665099260.822 9.00468
9296.3026.9903519364.752 6.751069422.9354.845165 9443.476.3240779532.456 5.92998
9700.0239.795492  9908.47.221537 9942.568.56668110026.148.53105210060.627.293348
10137.888.32506410151.987.244575 10281.59.41856610574.947.44520310853.6510.05504
10975.6714.0578410991.7213.6118211076.1518.5980511129.03 23.5264 11218.727.53218
#Mann= 3 , 0 , 0
8912.229  0.1168       08912.229  0.1168       0 11218.7  0.1168       0
#XS Ineff= 2 , 0
       09885.146        10190.49       0
Bank Sta=8912.229,11218.7
Exp/Cntr=0.3,0.1

Type RM Length L Ch R = 1 , 14.8026,0.000000,0.000000,0.000000
XS GIS Cut Line= 6
1193567.22326389 621768.402328641193483.02752116621827.450778022
1193435.97035044622002.2345550361193398.99685916622408.942959234
1193133.45996717623145.0515585691192797.33731905623911.411196262
#Sta/Elev= 30
8809.4248.803047 8856.464.4751858945.5833.1047339020.331 4.640929081.4892.484444
9190.5613.028864 9325.63  1.5096 9454.111.8589689514.0964.4023999583.6184.584191
9765.1572.6626069883.7134.0426549956.9442.976279 10033.74.41161610072.084.053526
10106.961.82674910375.125.07487110400.383.14840610461.716.13858110620.475.035393
10663.772.46705210773.134.49819410841.163.27490110853.064.01950710863.726.856001
10895.738.15742910917.0711.3637510977.22 12.140611009.5314.8845311121.1414.89416
#Mann= 3 , 0 , 0
8809.424   0.035       08809.424   0.035       011121.14   0.035       0
#XS Ineff= 2 , 0
       09834.192        10125.47       0
Bank Sta=8809.424,11121.14
Exp/Cntr=0.3,0.1